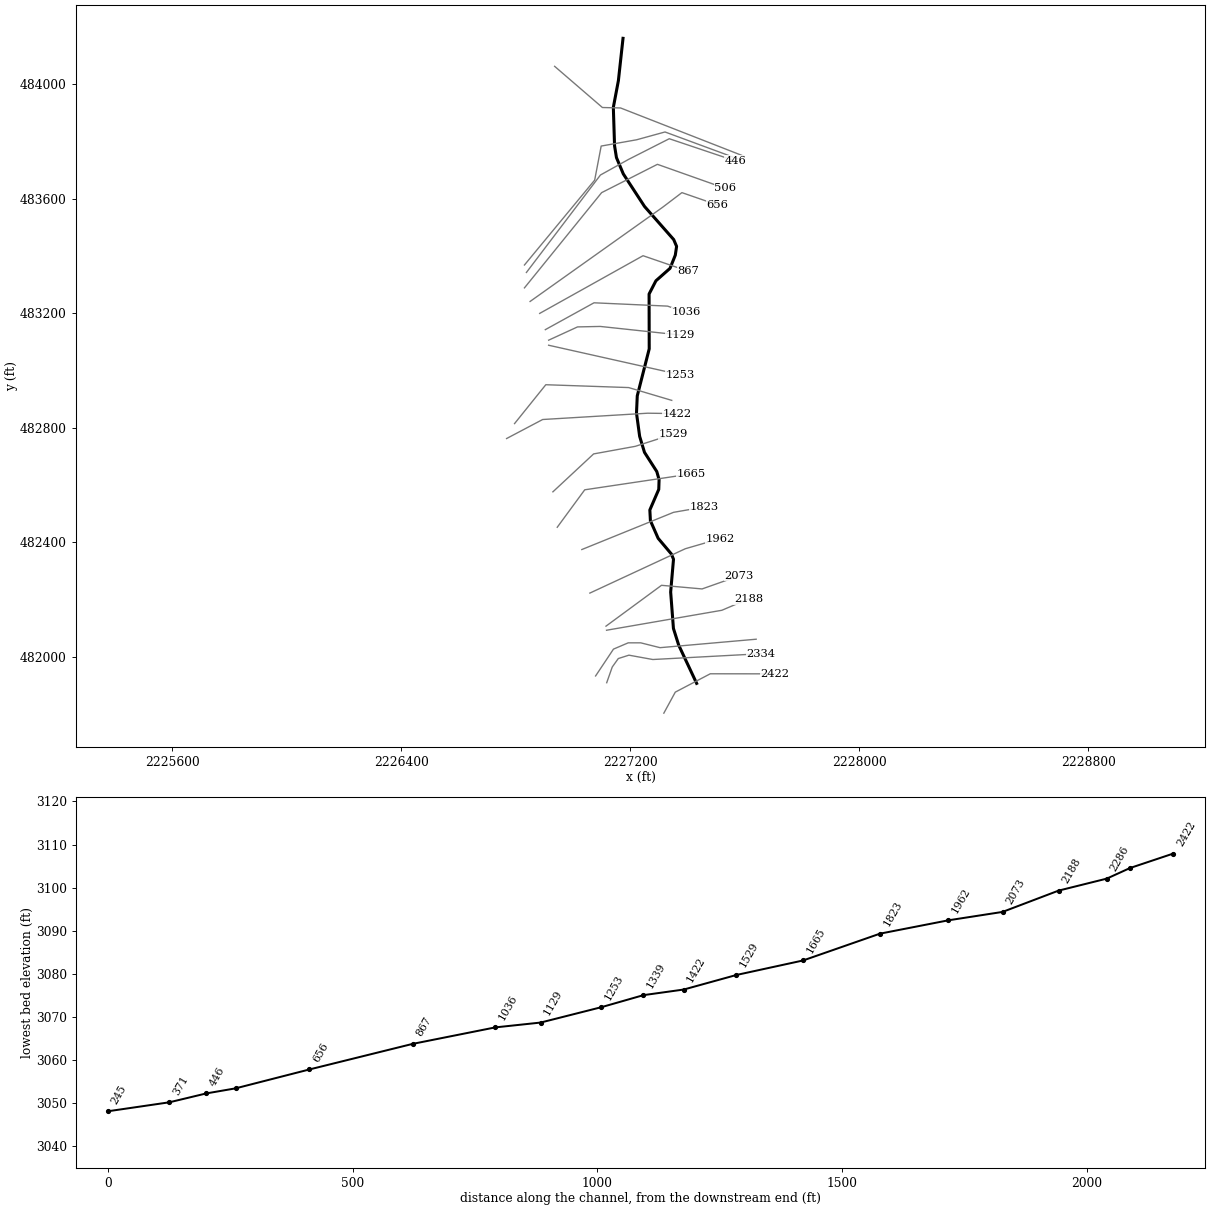
--- OLDFLDFK2.prj (project) ---

Proj Title=OLDFLDFK2
Current Plan=p01
Default Exp/Contr=0,0
English Units
Geom File=g01
Flow File=f01
Plan File=p01
Background Map Layer=Inundation Boundary (01pct Value_0)
BEGIN DESCRIPTION:
----------MODEL BY WOOD PLC 2021----------
Stream Name: Old Field Fork Upper Reach
Flood Zone: Enhanced Approximate
Pocahontas County, WV
HEC-RAS Version: RAS 6.1.0
Vertical Datum: NAVD88
Projection: NAD 1983 StatePlane West Virginia S FIPS 4702 (US Feet)
Terrain: 1-meter LIDAR (FEMA Region III 3DEP collected 2016-2018)
Land Use: 2019 NLCD
Hydrologic Method:
WV SIR2010-5033 regression equations weighted with gage ######
Model Notes:
Old Field Fork split at confluence with Crooked Fork which has a more dominant flow path
END DESCRIPTION:
DSS Export Rating Curves= 0
DSS Export Rating Curve Sorted= 0
DSS Export Volume Flow Curves= 0
DXF OffsetX= 0
DXF OffsetY= 0
DXF ScaleX= 0
DXF ScaleY= 0

--- OLDFLDFK2.p01 (plan) ---

Plan Title=Floodplain
Program Version=6.10
Short Identifier=Floodplain
Geom File=g01
Flow File=f01
Subcritical Flow
K Sum by GR= 0
Std Step Tol= 0.01
Critical Tol= 0.01
Num of Std Step Trials= 20
Max Error Tol= 0.3
Flow Tol Ratio= 0.001
Split Flow NTrial= 30
Split Flow Tol= 0.02
Split Flow Ratio= 0.02
Log Output Level= 0
Friction Slope Method= 1
Unsteady Friction Slope Method= 2
Unsteady Bridges Friction Slope Method= 1
Parabolic Critical Depth
Global Vel Dist= 0 , 0 , 0
Global Log Level= 0
CheckData=True
Encroach Param=-1 ,0,0, 0
Mapping Interval=1HOUR
Computation Time Step Use Courant=        0
Computation Time Step Use Time Series=    0
Computation Time Step Count To Double=0
Computation Time Step Max Doubling=0
Computation Time Step Max Halving=0
Computation Time Step Residence Courant=0
Run HTab= 0
Run UNet= 0
Run Sediment= 0
Run PostProcess= 0
Run WQNet= 0
Run RASMapper=-1
UNET Theta= 0
UNET Theta Warmup= 0
UNET ZTol= 0
UNET ZSATol= 0
UNET MxIter= 0
UNET Max Iter WO Improvement= 0
UNET MaxInSteps= 0
UNET DtIC= 0
UNET DtMin= 0
UNET MaxCRTS= 0
UNET WFStab= 0
UNET SFStab= 0
UNET WFX= 1
UNET SFX= 1
UNET Gravity=32.174
UNET 1D Methodology=Finite Difference
UNET DSS MLevel= 1
UNET Pardiso=0
UNET DZMax Abort= 0
UNET Use Existing IB Tables= 0
UNET Froude Reduction=False
UNET Froude Limit= 0
UNET Froude Power= 0
UNET D1 Cores= 0
UNET WindReference=Eulerian
UNET WindDragFormulation=Hsu (1988)
UNET D2 Coriolis=0
UNET D2 Cores= 0
UNET D2 Theta= 1
UNET D2 Theta Warmup= 1
UNET D2 Z Tol= 0.01
UNET D2 Volume Tol= 0.01
UNET D2 Max Iterations= 20
UNET D2 Equation= 0
UNET D2 RampUpFraction=0.1
UNET D2 TimeSlices= 1
UNET D2 Turbulence Formulation=Non-Conservative (original)
UNET D2 Eddy Viscosity=0.3
UNET D2 Transverse Eddy Viscosity=0.1
UNET D2 Smagorinsky Mixing=0
UNET D2 BCVolumeCheck=0
UNET D2 Cores=0
UNET D2 SolverType=PARDISO (Direct)
UNET D2 Minimum Iterations= 2147483647
UNET D2 Maximum Iterations= 2147483647
UNET D2 Restart Number= 10
UNET D2 Relaxation Coeff=1.3
UNET D2 SOR Precondition Iterations= 10
UNET D2 ILUT Maximum Fill= 8
UNET D2 ILUT Tolerance=1E-08
UNET D1D2 MaxIter= 0
UNET D1D2 ZTol=0.01
UNET D1D2 QTol=0.1
UNET D1D2 MinQTol=1
Write IC File= 0
Write IC File at Fixed DateTime=0
Write IC File at Sim End=0
Echo Input=False
Echo Parameters=False
Echo Output=False
Write Detailed= 0
HDF Write Warmup=0
HDF Write Time Slices=0
HDF Flush=0
HDF Compression= 1
HDF Chunk Size= 1
HDF Spatial Parts= 1
HDF Use Max Rows=0
HDF Fixed Rows= 1
Calibration Method= 0
Calibration Iterations= 20
Calibration Max Change=0.05
Calibration Tolerance=0.2
Calibration Maximum=1.5
Calibration Minimum=0.5
Calibration Optimization Method= 1
WQ AD Non Conservative
WQ ULTIMATE=-1
WQ Max Comp Step=1HOUR
WQ Output Interval=15MIN
WQ Output Selected Increments= 0
WQ Output face flow=0
WQ Output face velocity=0
WQ Output face area=0
WQ Output face dispersion=0
WQ Output cell volume=0
WQ Output cell surface area=0
WQ Output cell continuity=0
WQ Output cumulative cell continuity=0
WQ Output face conc=0
WQ Output face dconc_dx=0
WQ Output face courant=0
WQ Output face peclet=0
WQ Output face adv mass=0
WQ Output face disp mass=0
WQ Output cell mass=0
WQ Output cell source sink temp=0
WQ Output nsm pathways=0
WQ Output nsm derived pathways=0
WQ Create Restart=0
WQ Fixed Restart=0
WQ System Summary=0
WQ Write To DSS=0
Sorting and Armoring Iterations= 10
XS Update Threshold= 0.02
Bed Roughness Predictor= 0
Hydraulics Update Threshold= 0.02
Energy Slope Method= 1
Volume Change Method= 1
Sediment Retention Method= 0
Sediment TS Multiplier= 1
Warm Up Method= 0
XS Weighting Method= 0
Number of US Weighted Cross Sections= 1
Number of DS Weighted Cross Sections= 1
Upstream XS Weight=0
Main XS Weight=1
Downstream XS Weight=0
Number of DS XS's Weighted with US Boundary= 1
Upstream Boundary Weight= 1
Weight of XSs Associated with US Boundary= 0
Number of US XS's Weighted with DS Boundary= 1
Downstream Boundary Weight= 0.5
Weight of XSs Associated with DS Boundary= 0.5
Percentile Method= 0
Sediment Output Level= 3
Mass or Volume Output= 0
Output Increment Type= 1
Profile and TS Output Increment= 1
Transport Output Increment 1
XS Output Flag= 0
XS Output Increment= 10
Read HDF5 Sediment Hotstart= 0
Sediment Hotstart Type= 0
Write Gradation File= 0
Read Gradation Hotstart= 0
Write HDF5 File= 1
Write Binary Output= 1
Write DSS Sediment File= 0
DSS Sediment Output Type= 1
SV Curve= 0
Specific Gage Flag= 0
Subcell Erosion Methods= 0
Subcell Deposition Methods= 0
Advection Scheme= 1
Matrix Solver= 0
Implicit Weighting Factor= 1
Maximum Outer Loop Convergence Iterations= 5
Convergence Maximum Absolute= 0.001
Convergence RMSE= 0.0001
Grain Fractions Max Abs Error= 0.001
Max Subgrid Regions= 1
Max Subgrid Length Scale= 3.402823E+38
Initial Layer Thickness= 3.402823E+38
Min Layer Thickness= 3.402823E+38
Max Layer Thickness= 3.402823E+38
Number of Layers= 5

--- OLDFLDFK2.f01 (steady flow) ---

Flow Title=Flow
Program Version=6.00
Number of Profiles= 6
Profile Names=01pct,10pct,04pct,02pct,0_2pct,01plus
River Rch & RM=OLDFLDFK,Main            ,2422
     888     450     603     736    1330    1230
River Rch & RM=OLDFLDFK2,Main            ,2422
     888     450     603     736    1330    1230
Boundary for River Rch & Prof#=OLDFLDFK2,Main            , 1
Up Type= 0
Dn Type= 3
Dn Slope=0.01597
Boundary for River Rch & Prof#=OLDFLDFK2,Main            , 2
Up Type= 0
Dn Type= 3
Dn Slope=0.01597
Boundary for River Rch & Prof#=OLDFLDFK2,Main            , 3
Up Type= 0
Dn Type= 3
Dn Slope=0.01597
Boundary for River Rch & Prof#=OLDFLDFK2,Main            , 4
Up Type= 0
Dn Type= 3
Dn Slope=0.01597
Boundary for River Rch & Prof#=OLDFLDFK2,Main            , 5
Up Type= 0
Dn Type= 3
Dn Slope=0.01597
Boundary for River Rch & Prof#=OLDFLDFK2,Main            , 6
Up Type= 0
Dn Type= 3
Dn Slope=0.01597
DSS Import GetInterval= 0
DSS Import GetPeak= 0
DSS Import FillOption= 0

--- OLDFLDFK2.g01 (geometry) ---

Geom Title=Geometry
Program Version=6.10

River Reach=OLDFLDFK2       ,Main
Reach XY= 30
     2227431.388      481908.019     2227368.653      482041.544
     2227350.299      482099.771     2227340.629       482226.87
      2227350.57      482341.227     2227343.115      482359.577
      2227296.97      482414.217     2227269.881      482475.729
     2227267.883      482513.262     2227299.066      482585.135
     2227300.177      482619.228     2227292.143      482647.347
     2227249.173      482714.377     2227232.266      482770.162
     2227221.252      482851.4752227223.93951531482911.426202658
2227265.70154549483075.569138661     2227265.236      483266.868
2227289.10524159483313.0874578782227338.44815563      483356.625
     2227356.817      483402.525     2227361.341      483433.144
     2227351.274      483456.918     2227249.409      483572.411
     2227175.141      483686.168     2227151.232      483743.152
     2227144.633      483784.278     2227140.336      483918.338
     2227158.011      484011.691     2227174.176      484159.348

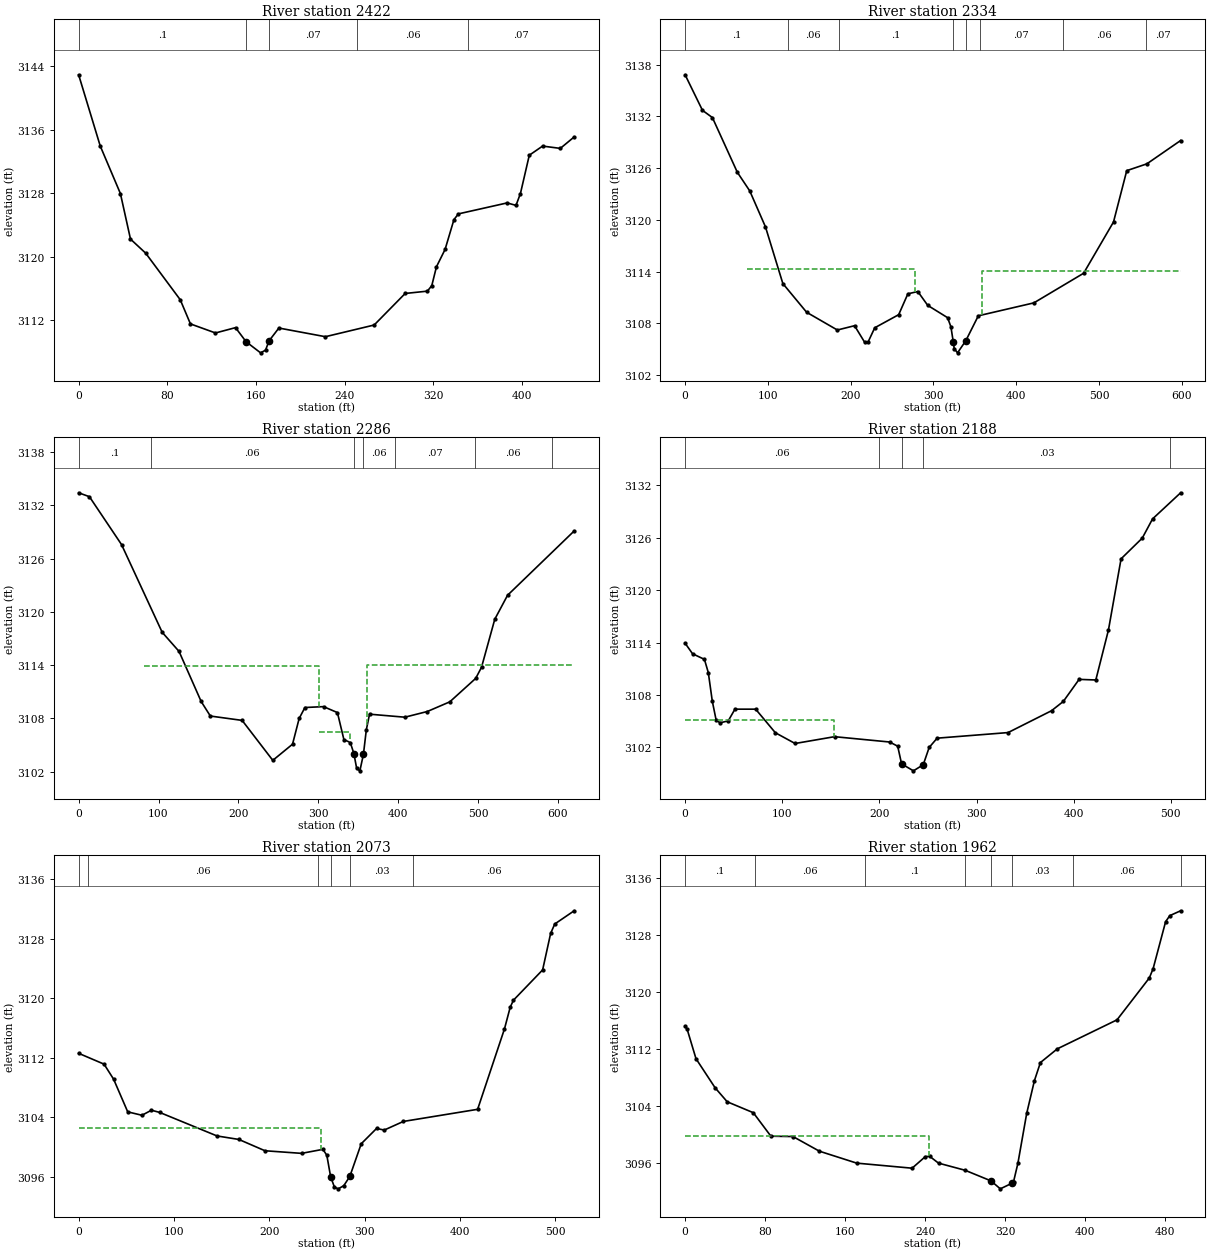
Type RM Length L Ch R = 1 ,2422    ,88.8,88.8,88.8
BEGIN DESCRIPTION:
xs 4
END DESCRIPTION:
XS GIS Cut Line= 4
2227316.79169966481804.0564107522227356.75511251481877.389852767
2227479.07911677 481941.504503282227704.66938191481941.261276108
#Sta/Elev= 30
       0 3142.91    19.5 3133.95    37.7 3127.97    46.8 3122.24    60.5 3120.47
    91.7 3114.61   100.9 3111.57   123.5 3110.43   141.6  3111.1   151.1 3109.33
   164.2 3107.93   168.7 3108.27   171.8 3109.43   180.7 3111.05   222.7 3109.96
   266.7 3111.43   294.7  3115.4   314.7 3115.69   318.7 3116.38   322.9 3118.75
   330.7 3120.94   338.7 3124.69   342.7 3125.41   386.7 3126.79   394.7 3126.48
   398.7 3127.97   406.7 3132.79   418.7 3133.94   434.7 3133.65   447.2 3135.09
#Mann= 5 ,-1,0
       0      .1       0   151.1    .045       0   171.8     .07       0
  251.62     .06       0  351.62     .07       0
Bank Sta=151.1,171.8
XS Rating Curve= 0 ,0
Exp/Cntr=0.5,0.3

Type RM Length L Ch R = 1 ,2334    ,46.9,47.6,48.6
BEGIN DESCRIPTION:
xs 3
END DESCRIPTION:
XS GIS Cut Line= 6
2227117.16878691481910.2907918462227136.57190483481965.125690311
2227157.66225039481994.6521740992227194.78125858482006.462767615
2227278.29902701481991.2777188092227657.08163333 482011.52445055
#Sta/Elev= 30
       0 3136.84      21 3132.71      33 3131.87    63.1 3125.52    78.1 3123.36
    97.1 3119.18   118.1  3112.6   146.8 3109.27   183.9 3107.21   204.7 3107.71
     217 3105.77   221.1 3105.83   229.1 3107.47     258 3108.99   269.1 3111.41
   281.1 3111.68   293.1 3110.07   317.1 3108.64   321.1 3107.58  323.883105.874
   325.1 3105.05   329.1 3104.56   339.1 3105.97   354.2 3108.86   421.3 3110.36
   481.4  3113.8   517.5 3119.75   533.5 3125.71   557.8  3126.5   598.6 3129.21
#Mann= 8 ,-1,0
       0      .1       0  124.45     .06       0  185.46      .1       0
  323.88    .045       0   339.1      .1       0  356.25     .07       0
  456.25     .06       0  556.25     .07       0
#XS Ineff= 3 ,-1
   74.37  277.18 3114.27  277.18   303.9 3108.05   359.1598.5716 3114.11
Permanent Ineff=
       F       F       F
Bank Sta=323.88,339.1
XS Rating Curve= 0 ,0
Exp/Cntr(USF)=0,0
Exp/Cntr=0.5,0.3

Type RM Length L Ch R = 1 ,2286    ,97.5,98.4,99.5
BEGIN DESCRIPTION:
xs 2
END DESCRIPTION:
XS GIS Cut Line= 6
2227078.36255107481933.9119788772227140.78997394482027.553113178
2227192.25041711482049.4870725642227236.11833589482049.487072564
2227303.60744169482032.6147961132227639.36574306482062.141279902
#Sta/Elev= 30
       0 3133.41    13.5 3132.97    53.7 3127.58   104.6  3117.7   125.7 3115.55
   153.4 3109.91   164.9 3108.27   204.7 3107.78   243.1 3103.28   267.8  3105.1
   276.1    3108   283.3 3109.23   306.6 3109.33     324 3108.66   332.1 3105.62
   340.1 3105.29   344.6 3104.05   348.1 3102.37   352.1  3102.1  356.533103.947
   360.2 3106.73   364.2 3108.48   408.4 3108.14   436.5 3108.78   464.7 3109.87
   497.1 3112.51   504.4 3113.76     521 3119.17     537 3121.87   620.4 3129.11
#Mann= 7 ,-1,0
       0      .1       0      90     .06       0   344.6    .045       0
  356.53     .06       0  395.77     .07       0  495.77     .06       0
  592.19     .07       0
#XS Ineff= 3 ,-1
   82.03   300.9 3113.85   300.9  339.61  3106.5   361.5 620.438    3114
Permanent Ineff=
       F       F       F
Bank Sta=344.6,356.53
XS Rating Curve= 0 ,0
Exp/Cntr(USF)=0,0
Exp/Cntr=0.5,0.3

Type RM Length L Ch R = 1 ,2188    ,118,114.5,110.5
XS GIS Cut Line= 3
 2227116.6018354482093.4666293522227519.39754981482163.098867215
2227612.59762203482202.735679537
#Sta/Elev= 30
       0 3113.93     7.7 3112.72    19.9 3112.08    23.9 3110.56      28 3107.29
      32  3105.1    36.1 3104.82    44.4 3105.04    51.3 3106.38    72.6 3106.38
    92.9 3103.68   113.2 3102.45   153.8 3103.23   210.5 3102.62   218.8 3102.14
   222.8 3100.12     235 3099.32   245.1 3100.02   251.2    3102   259.4 3103.06
   332.4  3103.7   377.1  3106.2   389.3 3107.27   405.5 3109.79   422.7 3109.72
   435.7 3115.44   448.7 3123.59   470.5 3125.96   481.1 3128.16     510 3131.15
#Mann= 5 ,-1,0
       0     .06       0     200     .03       0   222.8    .045       0
   245.1     .03       0  498.77     .06       0
#XS Ineff= 2 , 0
          152.99 3105.12
Permanent Ineff=
       F       F
Bank Sta=222.8,245.1
XS Rating Curve= 0 ,0
Exp/Cntr(USF)=0,0
Exp/Cntr=0.3,0.1

Type RM Length L Ch R = 1 ,2073    ,103,110.9,119
XS GIS Cut Line= 4
2227114.63794544482107.6964263182227308.66912462482250.267162326
2227450.39624681482237.6129549882227579.46916166482283.168101405
#Sta/Elev= 30
       0  3112.6    26.7 3111.14    36.7 3109.12    51.5 3104.73    66.4 3104.27
    76.4 3104.95    85.1 3104.65   145.2 3101.49   168.1 3101.02   195.5  3099.5
   233.9 3099.15   256.3 3099.69   260.4 3098.89   264.4    3096   268.4  3094.6
   272.4 3094.38   278.2 3094.81   284.5 3096.04   296.5 3100.44   312.6  3102.5
   320.6 3102.28   340.7 3103.44   418.6 3105.07   446.8 3115.89   452.8  3118.8
   456.2 3119.74   486.8 3123.81   495.2 3128.71   499.5 3129.98   519.9 3131.76
#Mann= 6 ,-1,0
       0      .1       0      10     .06       0  250.78     .03       0
   264.4    .045       0   284.5     .03       0  350.78     .06       0
#XS Ineff= 2 , 0
           254.2 3102.55
Permanent Ineff=
       F       F
Bank Sta=264.4,284.5
XS Rating Curve= 0 ,0
Exp/Cntr(USF)=0,0
Exp/Cntr=0.3,0.1

Type RM Length L Ch R = 1 ,1962    ,140.2,139.5,138.5
XS GIS Cut Line= 3
2227058.32562435482223.1231418412227391.60813037482377.861448206
2227514.60524568482413.570288136
#Sta/Elev= 30
       0 3115.16       2  3114.8    10.9 3110.65      30 3106.58    42.1 3104.62
    68.2 3103.09    85.8  3099.8   107.9 3099.75   134.3  3097.7   171.6 3096.03
     227 3095.32   240.2 3096.94   244.6 3096.98   253.4 3096.03     280 3095.03
   305.93093.544   315.2 3092.43   326.63093.196   328.4  3093.4   332.8 3096.01
   341.6    3103   349.3 3107.57   355.3 3110.11   372.2 3112.03   431.9 3116.09
   464.2 3121.95     468 3123.25   480.5 3129.83   484.7 3130.68   495.5 3131.36
#Mann= 8 ,-1,0
       0      .1       0      70     .06       0     180      .1       0
     280     .03       0   305.9    .045       0   326.6     .03       0
  387.45     .06       0  495.53      .1       0
#XS Ineff= 2 , 0
          244.19 3099.84
Permanent Ineff=
       F       F
Bank Sta=305.9,326.6
XS Rating Curve= 0 ,0
Exp/Cntr(USF)=0,0
Exp/Cntr=0.3,0.1

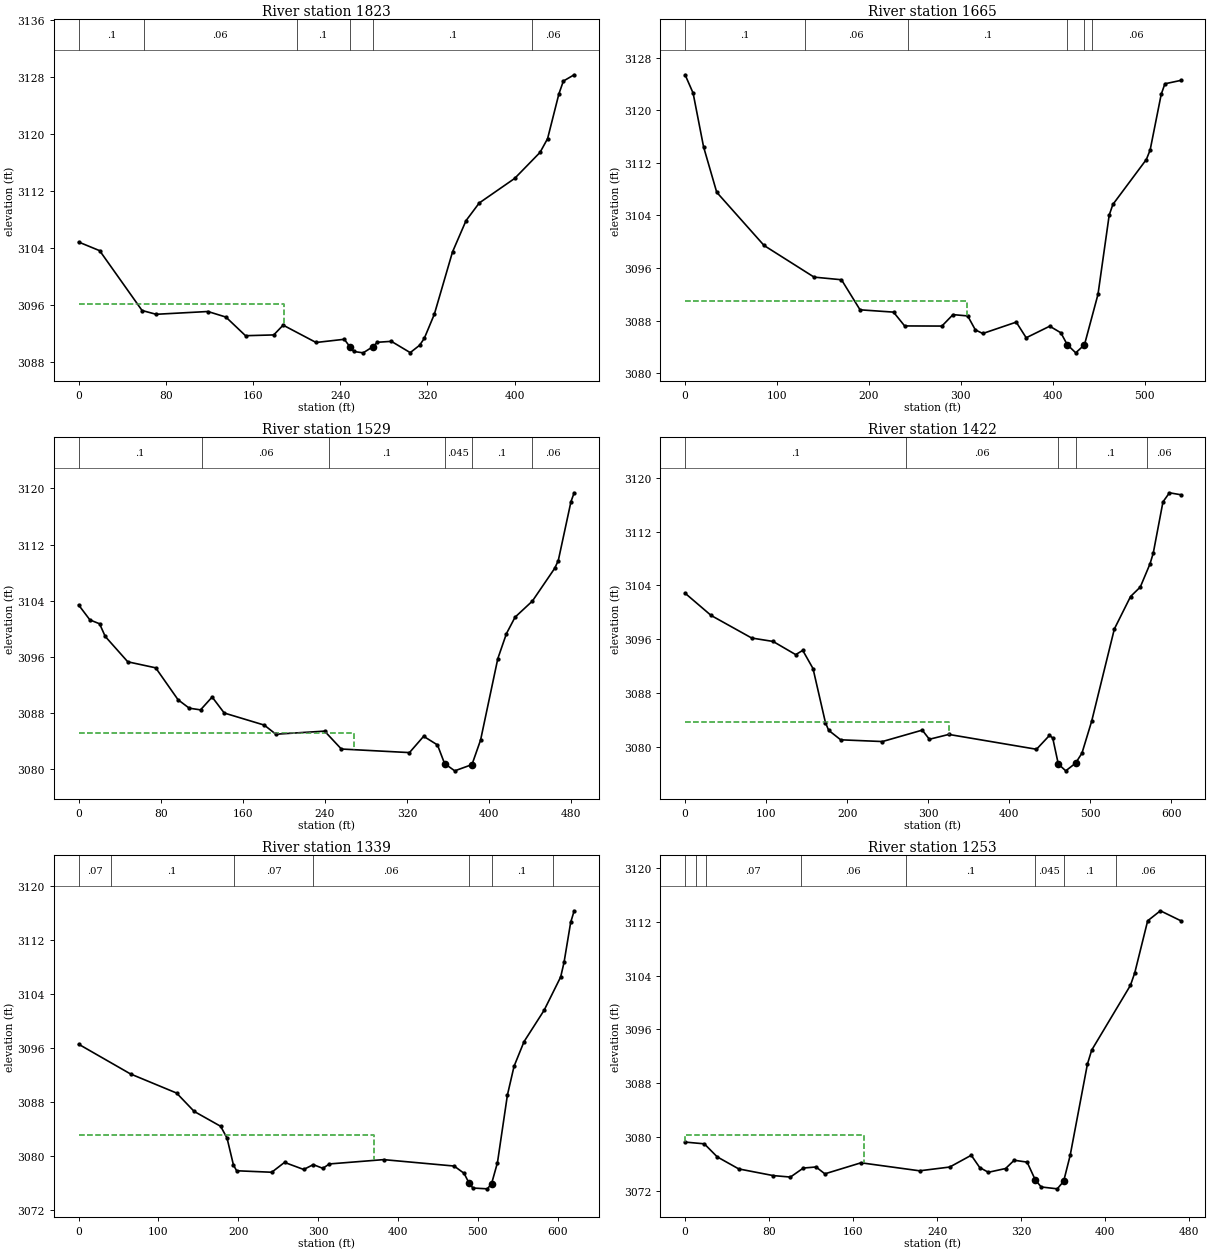
Type RM Length L Ch R = 1 ,1823    ,161.4,157.2,152.8
XS GIS Cut Line= 3
2227030.27656319482375.1220080612227350.84981575482505.038536731
2227457.98877121482523.598040826
#Sta/Elev= 30
       0 3104.86    19.3 3103.65    58.2 3095.27    71.1 3094.74   118.6 3095.13
   135.1 3094.35   153.1 3091.74     179 3091.85   187.6 3093.22   217.8 3090.79
   243.7 3091.24   248.7 3090.22   252.4 3089.53     261 3089.34   270.2 3090.22
     274 3090.82   286.9 3090.95   304.2 3089.37   312.8  3090.4   317.1 3091.37
   326.3 3094.74     343 3103.48   355.4 3107.86   367.5 3110.33     400 3113.77
   423.3 3117.42   430.2 3119.34   440.6 3125.62   444.7 3127.41   454.6 3128.29
#Mann= 6 ,-1,0
       0      .1       0      60     .06       0     200      .1       0
   248.7    .045       0   270.2      .1       0   415.9     .06       0
#XS Ineff= 2 , 0
          188.45 3096.14
Permanent Ineff=
       F       F
Bank Sta=248.7,270.2
XS Rating Curve= 0 ,0
Exp/Cntr(USF)=0,0
Exp/Cntr=0.3,0.1

Type RM Length L Ch R = 1 ,1665    ,133.9,136,137.2
XS GIS Cut Line= 3
2226944.37802616 482452.859156542227040.42733654482583.625085136
2227413.05237201482639.171674274
#Sta/Elev= 30
       0 3125.39     8.7 3122.61    20.1 3114.43    34.4 3107.53    85.9 3099.44
   140.3 3094.63   170.1 3094.23   190.3 3089.66   226.7 3089.31   238.8 3087.21
   279.3 3087.19   291.4 3088.93   307.4 3088.73   315.7 3086.61   323.8 3086.06
   360.2 3087.79     371 3085.41   396.6 3087.17   408.7 3086.17  415.633084.375
   424.9 3083.12   434.4 3084.35   449.1 3092.01   461.3 3104.06   465.3 3105.68
   501.7 3112.51   505.8 3113.94   517.9 3122.44   521.9 3124.02     539 3124.53
#Mann= 6 ,-1,0
       0      .1       0     130     .06       0  242.25      .1       0
  415.63    .045       0   434.4      .1       0  442.25     .06       0
#XS Ineff= 2 , 0
          306.59 3091.06
Permanent Ineff=
       F       F
Bank Sta=415.63,434.4
XS Rating Curve= 0 ,0
Exp/Cntr(USF)=0,0
Exp/Cntr=0.3,0.1

Type RM Length L Ch R = 1 ,1529    ,111.9,107.8,103
XS GIS Cut Line= 4
2226929.21978051482576.5360070742227071.46598245482708.858055389
 2227217.0202356482735.3224650522227350.99630952482778.327130754
#Sta/Elev= 30
       0  3103.4      11 3101.27    20.4 3100.72    25.9 3098.92    47.9  3095.3
    75.1 3094.44    96.9 3089.89   107.8 3088.69   118.8 3088.45   130.1 3090.28
   141.9    3088   180.9 3086.28   192.2 3084.98   239.7 3085.42     256 3082.87
   322.4 3082.36   336.2 3084.68   349.7 3083.45   356.6  3080.8   366.5 3079.76
   383.3 3080.65   391.7 3084.15   408.5 3095.76   416.9 3099.32   425.3 3101.66
   442.2 3103.96   463.9 3108.62   467.4 3109.72   479.8 3118.14   482.9 3119.39
#Mann= 6 ,-1,0
       0      .1       0     120     .06       0  244.28      .1       0
   356.6    .045       0   383.3      .1       0  442.22     .06       0
#XS Ineff= 2 , 0
          268.43 3085.22
Permanent Ineff=
       F       F
Bank Sta=356.6,383.3
XS Rating Curve= 0 ,0
Exp/Cntr(USF)=0,0
Exp/Cntr=0.3,0.1

Type RM Length L Ch R = 1 ,1422    ,88.3,82.3,75.2
XS GIS Cut Line= 4
2226767.42355879482762.5396460062226893.46031945482828.955853828
2227260.29925188482850.943045362 2227361.9243476482849.609058147
#Sta/Elev= 30
       0 3102.82    32.1 3099.51    82.2 3096.15   108.6 3095.64   136.5 3093.68
   145.2 3094.31   157.9  3091.6   173.2 3083.56   177.2 3082.41     192    3081
   243.5 3080.74   292.7 3082.44   301.5 3081.08   325.5  3081.8   433.7 3079.59
   449.7 3081.65   453.7 3081.28   460.6  3077.4   469.8 3076.38   481.9 3077.52
   489.8 3079.01   501.8 3083.77   529.8  3097.5   549.8 3102.33   561.8 3103.74
   573.8 3107.19   577.8 3108.79   589.8 3116.42   597.8 3117.77   611.6 3117.48
#Mann= 5 ,-1,0
       0      .1       0  272.47     .06       0   460.6    .045       0
   481.9      .1       0  569.96     .06       0
#XS Ineff= 2 , 0
          326.14 3083.63
Permanent Ineff=
       F       F
Bank Sta=460.6,481.9
XS Rating Curve= 0 ,0
Exp/Cntr=0.3,0.1

Type RM Length L Ch R = 1 ,1339    ,84.6,85.9,87.2
XS GIS Cut Line= 4
2226795.24370659482814.7156940412226904.40939645482950.345793564
2227193.86387714 482940.42163994 2227344.3802071482895.762948634
#Sta/Elev= 30
       0 3096.52      65 3092.11   122.7 3089.28   144.7 3086.56   177.9 3084.35
   185.9  3082.6   193.9 3078.62   197.9 3077.76   241.9 3077.54   257.9    3079
   281.9 3077.95   293.9 3078.67   305.9 3078.12     314 3078.77     382 3079.41
   470.3 3078.46   482.8 3077.38   489.2 3075.89   493.9  3075.2     512 3075.08
   517.3 3075.87   524.6 3078.96   537.1    3089   545.4 3093.25   557.9  3096.9
     583 3101.54   603.8 3106.49     608 3108.65   616.3 3114.57   620.7  3116.3
#Mann= 7 ,-1,0
       0     .07       0      40      .1       0  194.11     .07       0
  294.11     .06       0   489.2    .045       0   517.3      .1       0
  593.73     .06       0
#XS Ineff= 2 , 0
          369.52    3083
Permanent Ineff=
       F       F
Bank Sta=489.2,517.3
XS Rating Curve= 0 ,0
Exp/Cntr(USF)=0,0
Exp/Cntr=0.3,0.1

Type RM Length L Ch R = 1 ,1253    ,122.2,124.3,126.4
XS GIS Cut Line= 2
2226914.29029038483088.1732698052227374.86409198482985.180635779
#Sta/Elev= 30
       0 3079.24    18.3 3078.98    30.6 3077.04    51.1 3075.25    83.9 3074.26
   100.3 3074.04   112.6 3075.38   124.7 3075.54   133.1 3074.52   167.5 3076.16
   223.3 3074.97     252 3075.53   272.5 3077.28   280.6 3075.45   288.8 3074.75
   305.2 3075.31   313.4 3076.54   325.7 3076.26  333.463073.625   339.1 3072.57
   354.4 3072.29  360.473073.406   366.7 3077.26   383.1 3090.81   387.2 3092.91
   424.1 3102.54   428.2 3104.39   440.5 3112.13   452.6 3113.62   471.9 3112.15
#Mann= 8 ,-1,0
       0     .07       0      10     .06       0      20     .07       0
     110     .06       0     210      .1       0  333.46    .045       0
  360.47      .1       0     410     .06       0
#XS Ineff= 2 , 0
          170.42 3080.36
Permanent Ineff=
       F       F
Bank Sta=333.46,360.47
XS Rating Curve= 0 ,0
Exp/Cntr(USF)=0,0
Exp/Cntr=0.3,0.1

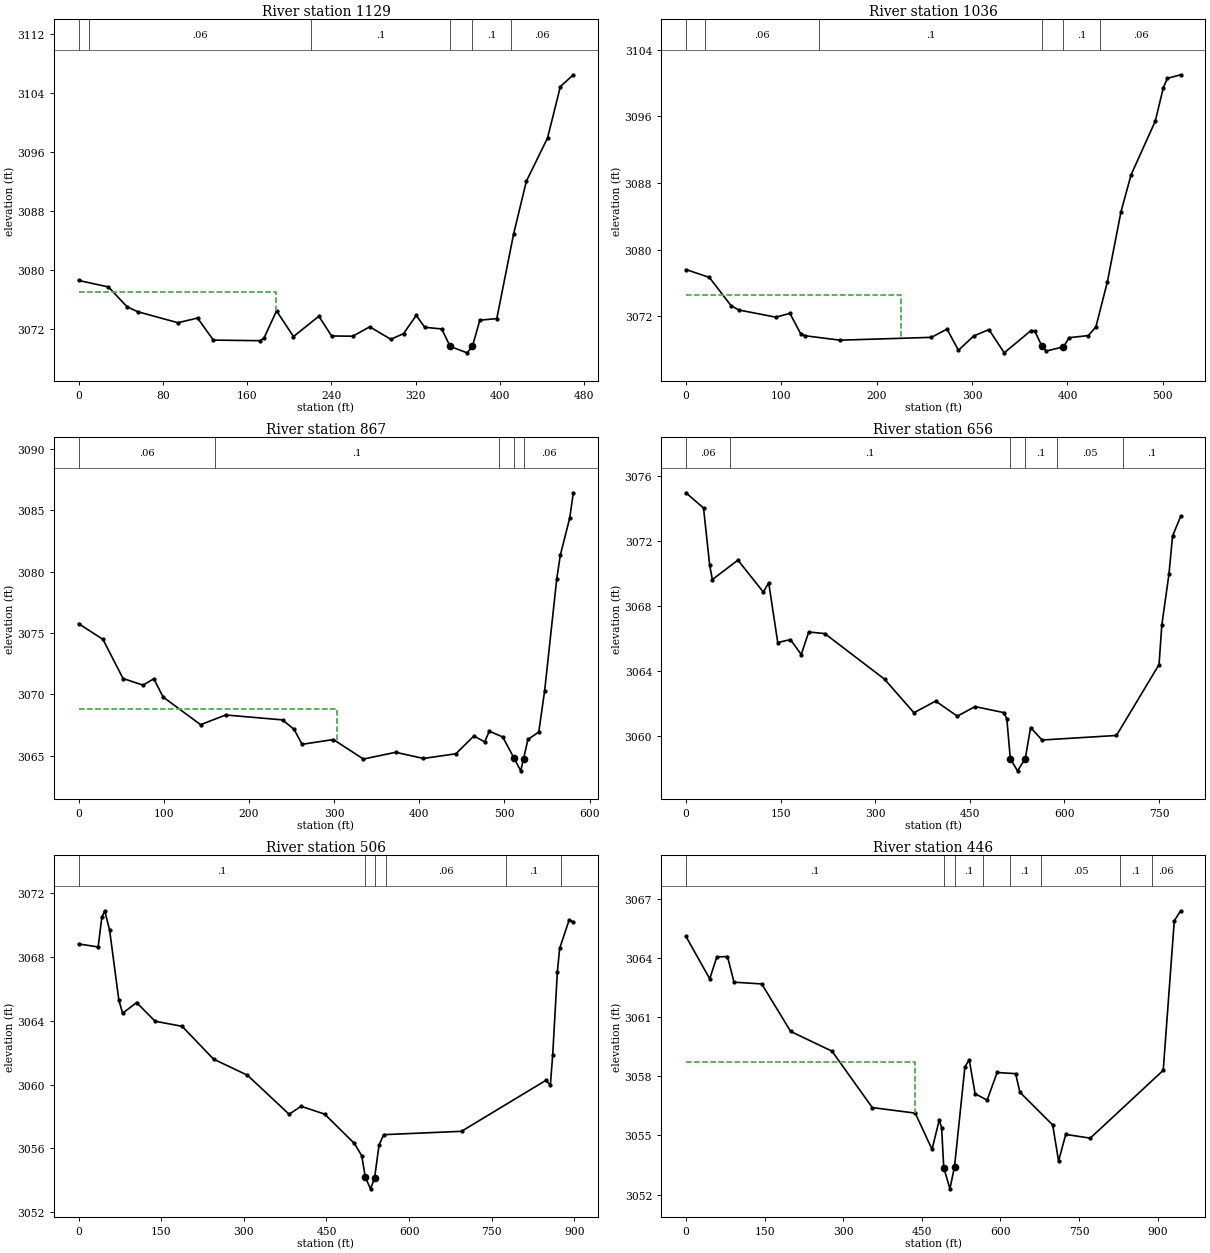
Type RM Length L Ch R = 1 ,1129    ,91.4,92.6,93.7
XS GIS Cut Line= 4
2226914.33355008483105.8242003342227015.22911192483152.136917245
2227094.62234091483153.7909428492227372.49864237483124.018481978
#Sta/Elev= 30
       0 3078.55    28.4 3077.66      46 3074.98      56 3074.31    94.3 3072.81
     113 3073.44     128 3070.45     172 3070.37     176 3070.69     188 3074.42
   204.1 3070.93   228.2 3073.69   240.3 3071.01   260.4 3070.98   276.5 3072.25
   296.6 3070.56   308.7 3071.34   320.7  3073.8   328.8 3072.19   344.9 3071.96
   352.9 3069.59     369 3068.72   374.1  3069.6   381.1 3073.15   397.2 3073.37
   413.2 3084.87   425.3 3092.02   445.4 3097.89   457.6 3104.87   469.9 3106.47
#Mann= 6 ,-1,0
       0     .07       0      10     .06       0  220.43      .1       0
   352.9    .045       0   374.1      .1       0  410.43     .06       0
#XS Ineff= 2 , 0
          187.89 3076.96
Permanent Ineff=
       F       F
Bank Sta=352.9,374.1
XS Rating Curve= 0 ,0
Exp/Cntr(USF)=0,0
Exp/Cntr=0.3,0.1

Type RM Length L Ch R = 1 ,1036    ,175,169.1,161.9
XS GIS Cut Line= 4
2226902.71808431483142.5626383362227072.82951354483236.297507506
 2227329.7324883483224.7253014362227393.37962169483202.738109902
#Sta/Elev= 30
       0  3077.6    24.5 3076.66    47.2 3073.28    55.2 3072.75    94.3 3071.88
     109 3072.34   120.4 3069.87     125 3069.65   161.5 3069.12   257.4 3069.46
   273.7 3070.45   285.7 3067.91   301.7 3069.63   317.7 3070.39   333.7  3067.6
   361.7 3070.27   365.7 3070.22  373.22  3068.4   377.8 3067.82   395.8 3068.32
   401.8 3069.42   421.8 3069.67   429.8 3070.71   441.8  3076.1   456.1 3084.53
   466.7 3088.97   492.1 3095.42   500.5 3099.43   504.8 3100.55   518.7 3100.98
#Mann= 6 ,-1,0
       0     .07       0      20     .06       0     140      .1       0
  373.22    .045       0   395.8      .1       0  434.23     .06       0
#XS Ineff= 2 , 0
          225.74 3074.57
Permanent Ineff=
       F       F
Bank Sta=373.22,395.8
XS Rating Curve= 0 ,0
Exp/Cntr(USF)=0,0
Exp/Cntr=0.3,0.1

Type RM Length L Ch R = 1 ,867     ,198.3,210.9,222.6
XS GIS Cut Line= 3
2226883.04533399483199.2664480812227244.09816338483400.622833706
2227402.63738655483346.233465175
#Sta/Elev= 30
       0 3075.76    28.6 3074.48    52.2 3071.29    75.7 3070.75    88.3 3071.27
    99.3 3069.78   143.3 3067.53   172.8 3068.32   239.5 3067.92   253.2 3067.14
   262.4 3065.93   299.2 3066.32   334.5 3064.73   372.3 3065.28     405 3064.78
   443.1 3065.16   464.2 3066.61   476.9 3066.13   482.3    3067   498.1 3066.53
     511 3064.85   519.2 3063.77   522.6 3064.77   527.7 3066.33   540.4 3066.93
   547.3 3070.28   561.5 3079.39   565.7 3081.33   576.8 3084.38     581 3086.42
#Mann= 5 ,-1,0
       0     .06       0     160      .1       0   493.4     .06       0
     511    .045       0   522.6     .06       0
#XS Ineff= 2 , 0
          302.94 3068.78
Permanent Ineff=
       F       F
Bank Sta=511,522.6
XS Rating Curve= 0 ,0
Exp/Cntr(USF)=0,0
Exp/Cntr=0.3,0.1

Type RM Length L Ch R = 1 ,656     ,153.1,150.7,148
XS GIS Cut Line= 4
2226849.48593638483240.926389934 2227312.3741792483569.577042333
 2227379.9179727483620.8093458712227504.43921605483577.722434817
#Sta/Elev= 30
       0 3074.98    27.9 3074.04    37.6 3070.52    41.9 3069.63    82.4 3070.83
   122.6 3068.86   131.2 3069.43   145.5 3065.75   165.6 3065.93   182.8 3065.01
   194.6  3066.4   220.1  3066.3   314.8 3063.49   361.4 3061.42   395.8 3062.14
   430.1 3061.21   458.3  3061.8   503.7 3061.43   508.6 3061.06  514.18 3058.58
   525.6 3057.84  537.85 3058.59   546.3 3060.51   564.4 3059.74   682.4 3060.02
   749.9 3064.39   754.3 3066.83   765.6 3069.96   771.3 3072.31   784.2 3073.53
#Mann= 6 ,-1,0
       0     .06       0      70      .1       0  514.18    .045       0
  537.85      .1       0  587.69     .05       0  692.47      .1       0
Bank Sta=514.18,537.85
XS Rating Curve= 0 ,0
Exp/Cntr(USF)=0,0
Exp/Cntr=0.3,0.1

Type RM Length L Ch R = 1 ,506     ,59.2,59.7,60.4
XS GIS Cut Line= 4
2226829.81318606483288.3724348232227099.39705418483620.707516853
2227294.35893216483719.5752362182227531.52935895483635.620734176
#Sta/Elev= 30
       0 3068.83    35.5 3068.64    42.2  3070.5    47.4 3070.91    56.3  3069.7
    73.1  3065.3    79.9 3064.48   105.3 3065.15   138.8 3063.98   187.9 3063.66
     245  3061.6   306.5 3060.59   382.2 3058.14   403.8 3058.64   446.7 3058.15
   500.6 3056.31     514 3055.54   520.5 3054.18     530 3053.46537.3398 3054.15
   545.4  3056.2   553.8 3056.86   695.1 3057.07   847.9 3060.26   856.4 3059.98
   860.6 3061.84   869.1 3067.06   873.3 3068.55   890.3 3070.31   898.1 3070.23
#Mann= 6 ,-1,0
       0      .1       0   520.5    .045       0537.3398      .1       0
  557.93     .06       0  776.53      .1       0  876.53     .06       0
Bank Sta=520.5,537.3398
XS Rating Curve= 0 ,0
Exp/Cntr(USF)=0,0
Exp/Cntr=0.3,0.1

Type RM Length L Ch R = 1 ,446     ,80.5,75.5,69.9
XS GIS Cut Line= 5
2226836.66954291483342.1690073462227095.26381391483682.283952931
 2227192.8470864483736.4190964282227335.73256758483808.937006683
2227567.68280513483731.062717229
#Sta/Elev= 30
       0 3065.09    45.4 3062.94    58.9 3064.05    79.2 3064.07    91.7 3062.77
   144.6 3062.68   199.8 3060.27   278.7 3059.27   355.5 3056.41   437.4 3056.13
   469.5 3054.29   483.2 3055.78   487.8 3055.39   491.8 3053.37   503.6 3052.29
   512.4 3053.42   532.2 3058.48   540.5 3058.83   551.6 3057.11   574.6 3056.79
   593.6 3058.19   628.9 3058.13   637.1 3057.19   699.6 3055.53   710.9  3053.7
   724.5 3055.05   771.3 3054.86   910.5  3058.3   931.6 3065.88   943.8 3066.39
#Mann= 8 ,-1,0
       0      .1       0   491.8    .045       0   512.4      .1       0
  567.26     .06       0  617.26      .1       0  677.26     .05       0
  828.81      .1       0  888.81     .06       0
#XS Ineff= 2 , 0
          437.18 3058.73
Permanent Ineff=
       F       F
Bank Sta=491.8,512.4
XS Rating Curve= 0 ,0
Exp/Cntr(USF)=0,0
Exp/Cntr=0.3,0.1

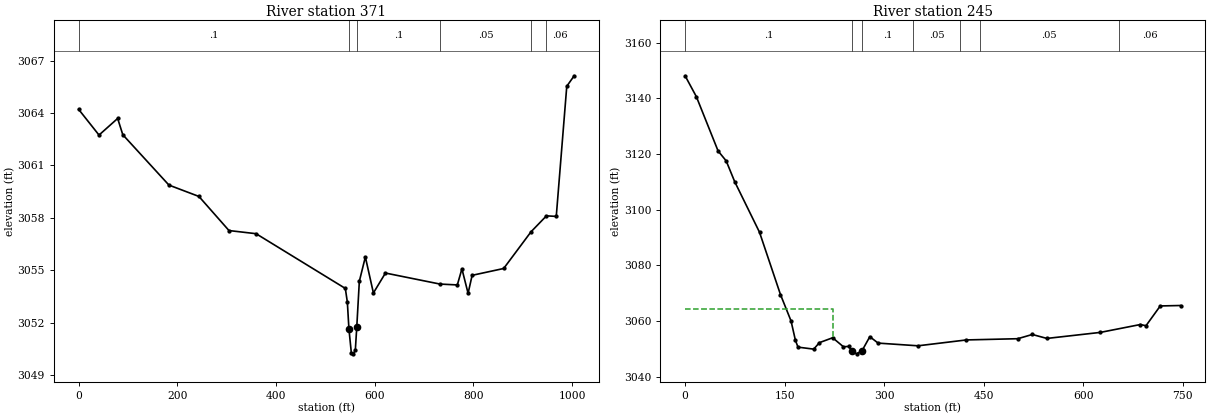
Type RM Length L Ch R = 1 ,371     ,126.1,125.5,126.1
XS GIS Cut Line= 6
2226829.81318606483368.2206567092227075.14395476483664.469132111
2227097.88146578483783.3530201742227221.55403929483805.233167053
2227320.87425438483832.5087867642227574.18228694483739.050168141
#Sta/Elev= 30
       0 3064.21    41.3 3062.74    79.1 3063.69    89.5 3062.76     183 3059.88
   243.8 3059.23   304.7 3057.28   359.6  3057.1   540.5 3053.97   544.6 3053.19
  547.76 3051.67   552.7 3050.28   556.8 3050.23   560.8 3050.45  563.65 3051.74
   568.9 3054.38   581.1 3055.77   597.4 3053.71   621.8 3054.85   732.3 3054.22
   767.5 3054.17   776.8 3055.09   789.3 3053.69   797.5 3054.72   861.4 3055.11
   916.9 3057.21   948.1 3058.12     968 3058.09   989.3 3065.53  1004.3 3066.13
#Mann= 6 ,-1,0
       0      .1       0  547.76    .045       0  563.65      .1       0
   732.3     .05       0   916.9      .1       0   948.1     .06       0
Bank Sta=547.76,563.65
XS Rating Curve= 0 ,0
Exp/Cntr(USF)=0,0
Exp/Cntr=0.3,0.1

Type RM Length L Ch R = 1 ,245     ,252,,260.1
XS GIS Cut Line= 4
2226935.26341792484061.6018650522227102.17263936483917.874479925
2227165.53632527483916.3290241712227596.71848065 483747.87434698
#Sta/Elev= 30
       0 3148.13      17 3140.61    49.7  3121.1    61.9 3117.53    74.7 3110.07
   112.1 3091.88   143.7 3069.46   159.6 3059.99   166.2 3053.03   170.1 3050.56
   193.8 3049.84   202.3 3052.17   222.3 3053.93   238.5  3050.7   246.3 3050.81
  251.17  3049.3   258.3 3048.15   266.7 3049.32   278.3 3054.32   290.8 3052.01
   350.9 3051.04   423.9 3053.15   501.2 3053.59   523.1 3055.11   545.1 3053.69
   625.7 3055.86   685.9 3058.69   694.4 3058.26   715.9 3065.37   746.6 3065.53
#Mann= 7 ,-1,0
       0      .1       0  251.17    .045       0   266.7      .1       0
  343.65     .05       0  413.65      .1       0  443.65     .05       0
  653.65     .06       0
#XS Ineff= 2 , 0
          222.65 3064.12
Permanent Ineff=
       F       F
Bank Sta=251.17,266.7
XS Rating Curve= 0 ,0
Exp/Cntr(USF)=0,0
Exp/Cntr=0.3,0.1
LCMann Table=0

Chan Stop Cuts=-1
Use User Specified Reach Order=0
Composite Channel Slope=5